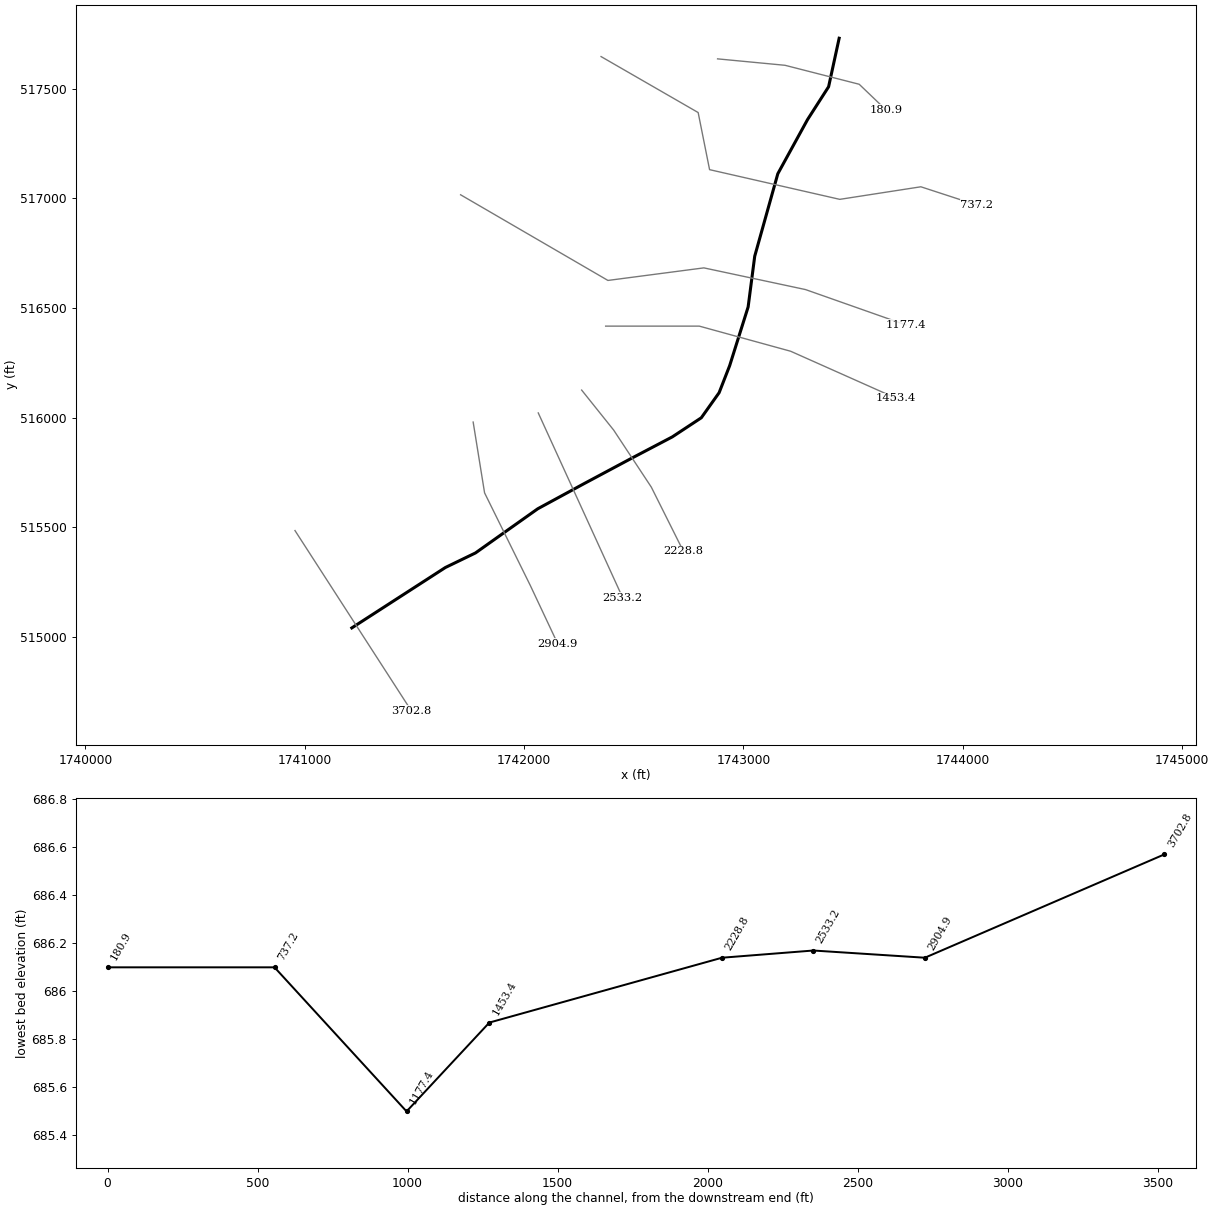
--- ROCKYFK.prj (project) ---

Proj Title=ROCKYFK
Current Plan=p01
Default Exp/Contr=0,0
English Units
Geom File=g01
Flow File=f01
Plan File=p01
BEGIN DESCRIPTION:
END DESCRIPTION:
DSS Export Rating Curves= 0
DSS Export Rating Curve Sorted= 0
DSS Export Volume Flow Curves= 0
DXF OffsetX= 0
DXF OffsetY= 0
DXF ScaleX= 0
DXF ScaleY= 0

--- ROCKYFK.p01 (plan) ---

Plan Title=Floodplain
Program Version=4.00
Geom File=g01
Flow File=f01
K Sum by GR=0
Std Step Tol=0.01
Critical Tol=0.01
Num of Std Step Trials=20
Max Error Tol=0.3
Flow Tol Ratio=0.001
Split Flow NTrial=30
Split Flow Tol=0.02
Split Flow Ratio=0.02
Log Output Level=0
Friction Slope Method=1
Unsteady Friction Slope Method=2
Unsteady Bridges Friction Slope Method=1
Global Log Level=0
CheckData=False
Run HTab=0
Run UNet=0
Run PostProcess=0
UNET Theta=0
UNET Theta Warmup=0
UNET ZTol=0
UNET ZSATol=0
UNET MxIter=0
UNET MaxInSteps=0
UNET DtIC=0
UNET DtMin=0
UNET MaxCRTS=0
UNET WFStab=0
UNET SFStab=0
UNET WFX=0
UNET SFX=0
UNET DSS MLevel=0
UNET DZMax Abort=0
UNET Convert EG Bridges=0
UNET Use Existing IB Tables=0
UNET Froude Limit=0
UNET Froude Power=0
Write IC File=0
Echo Input=False
Echo Output=False
Write Detailed=0

--- ROCKYFK.f01 (steady flow) ---

Flow Title=NFF Regression Equation
Program Version=4.10
Number of Profiles= 1
Profile Names=P100yr
River Rch & RM=ROCKYFK,Main            ,3702.8
878.8217
River Rch & RM=ROCKYFK,Main            ,2904.9
895.5905
River Rch & RM=ROCKYFK,Main            ,737.2
987.1938
Boundary for River Rch & Prof#=ROCKYFK,Main            , 1
Up Type= 0
Dn Type= 1
Dn Known WS=692.2
DSS Import GetInterval= 0
DSS Import GetPeak= 0
DSS Import FillOption= 0

--- ROCKYFK.g01 (geometry) ---

Geom Title=USGS 10m DEM
Program Version=4.10

River Reach=ROCKYFK         ,Main
Reach XY= 17
     1741214.595      515041.239     1741641.376       515316.76
     1741778.554      515383.097     1741918.083      515482.183
     1742062.452      515584.444     1742272.989      515698.736
      1742492.55      515816.036     1742676.019      515912.282
     1742808.357      515999.504     1742889.564      516113.796
     1742937.687      516237.111     1743021.902      516504.795
     1743051.979      516736.386     1743157.248      517112.346
     1743292.593      517358.976     1743388.849      517509.022
     1743437.029      517730.345

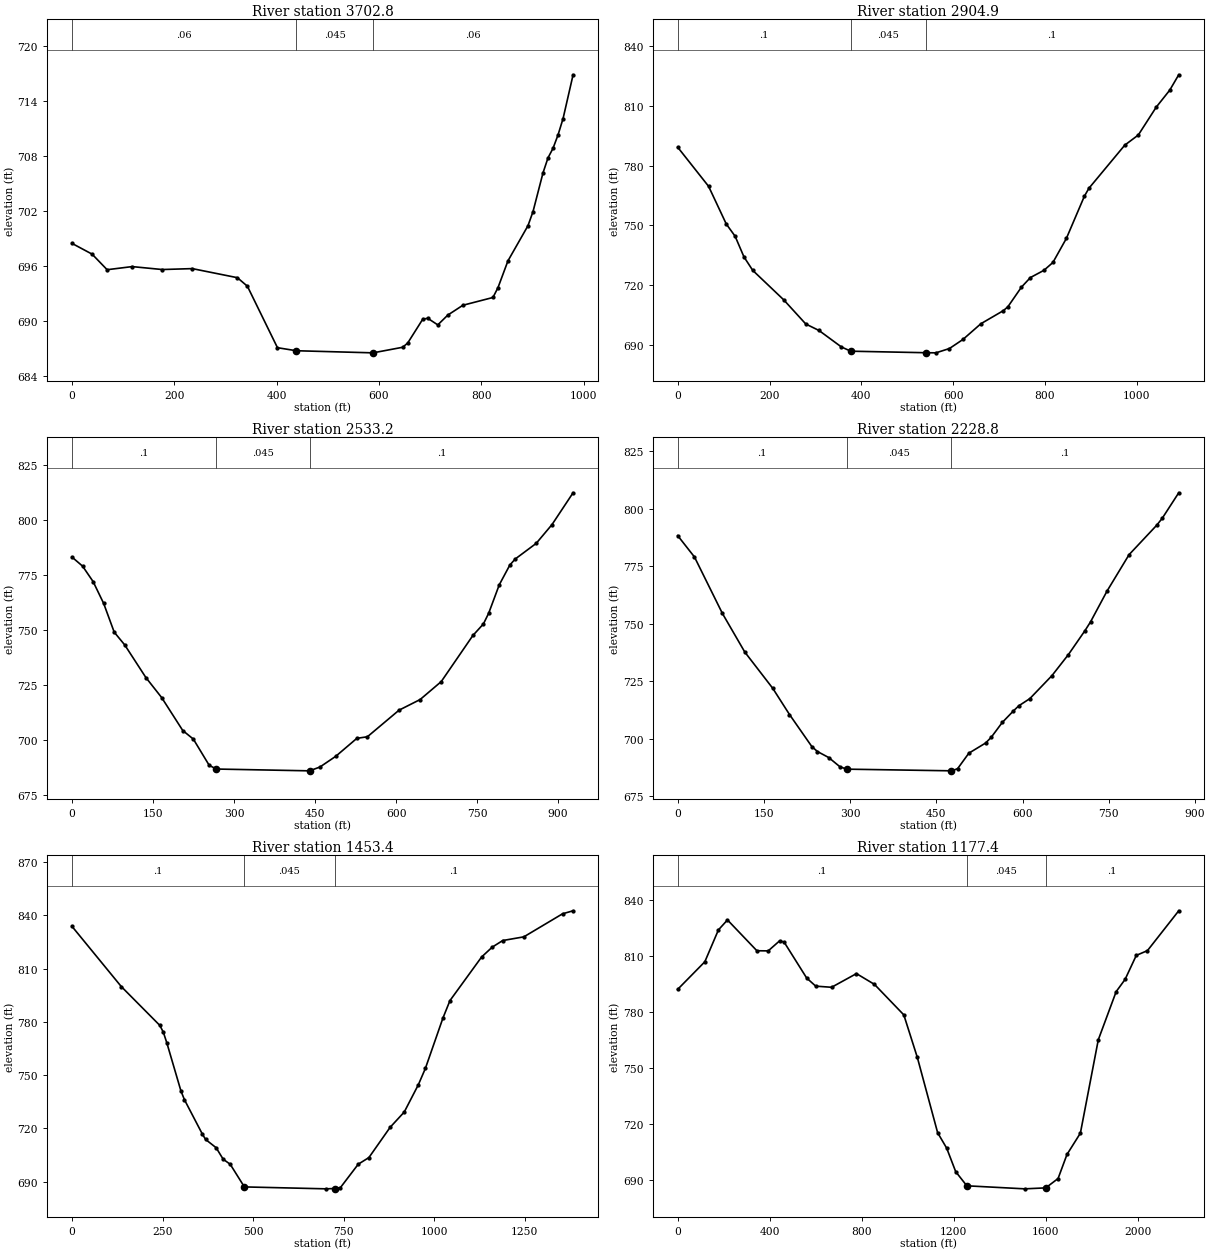
Type RM Length L Ch R = 1 ,3702.8  ,808.2,797.8,787.4
XS GIS Cut Line= 2
     1740955.468      515485.168     1741486.718      514662.251
#Sta/Elev= 30
       0  698.51    39.2  697.34    68.6  695.64   117.5  695.98   176.3  695.66
   235.1  695.76   323.2  694.77   342.8  693.84   401.6  687.13   438.5   686.8
   587.7  686.57   588.5  686.57   646.5  687.18   656.3  687.65   685.6  690.24
   695.4  690.34     715  689.62   734.6  690.69     764  691.76   822.8  692.61
   832.6  693.67   852.2  696.61   891.3  700.44   901.1  701.97   920.7  706.21
   930.5  707.85   940.3  708.89   950.1  710.35   959.9  712.13   979.5  716.91
#Mann= 3 , 0 , 0
       0     .06       0   438.5    .045       0   588.5     .06       0
Bank Sta=438.5,588.5
XS Rating Curve= 0 ,0
Exp/Cntr=0.3,0.1

Type RM Length L Ch R = 1 ,2904.9  ,374.3,371.8,369.1
XS GIS Cut Line= 4
     1741767.968       515979.96     1741820.051      515657.043
     1742028.384      515235.168     1742153.384      514969.543
#Sta/Elev= 30
       0   789.2    67.3   769.6   105.8  750.72   125.1  744.57   144.3  734.24
   163.5  727.46   230.9  712.71     279  700.59   307.8  697.34   356.5  689.09
     377 686.963     540   686.2   562.4  686.14   591.8   688.3   621.2  692.84
   660.4  700.74   709.4  707.31   719.2  709.26   748.6  719.06   768.2  723.88
   797.6   727.5   817.2  731.44   846.5   743.5   885.7  764.64   895.5   768.6
   973.7  790.25  1003.1  795.31  1042.2  809.29  1071.6   817.8  1091.2  825.51
#Mann= 3 , 0 , 0
       0      .1       0     377    .045       0     540      .1       0
Bank Sta=377,540
XS Rating Curve= 0 ,0
Exp/Cntr=0.3,0.1

Type RM Length L Ch R = 1 ,2533.2  ,290.6,304.4,318.6
XS GIS Cut Line= 2
     1742064.843      516021.626     1742450.259      515177.876
#Sta/Elev= 30
       0  783.14    19.5  779.06    39.1  772.01    58.6  762.11    78.1  749.09
    97.6  743.29   136.7  728.51     166  719.39     205  704.46   224.6  700.57
   253.9  688.69     267 686.989   439.4  686.17     440 686.201   458.9   687.9
   488.2  692.76   527.3  700.92   546.8  701.63   605.4   713.7   644.4  718.52
   683.5  726.66   742.1  747.59   761.6  752.83   771.4  757.72   790.9  770.57
   810.4   779.5   820.2  782.24   859.3  789.38   888.6  797.92   927.6  812.34
#Mann= 3 , 0 , 0
       0      .1       0     267    .045       0     440      .1       0
Bank Sta=267,440
XS Rating Curve= 0 ,0
Exp/Cntr=0.3,0.1

Type RM Length L Ch R = 1 ,2228.8  ,710,775.4,840.4
XS GIS Cut Line= 4
     1742262.759      516125.793     1742408.593      515943.501
     1742580.468      515683.085     1742726.301      515391.418
#Sta/Elev= 30
       0  788.34    29.2  779.05    77.8  754.52   116.7  737.76   165.4  721.98
   194.5  710.61   233.4  696.67   243.2  694.52   262.7  691.92   282.2  687.92
     294 686.872     475 686.154   477.2  686.14     487  687.11   506.5  693.81
   535.7  698.24   545.5  700.74   564.6  707.15   583.8  712.12   593.4   714.4
   612.6  717.52     651   727.5   679.7  736.66   708.5  747.06   718.1  750.84
   746.9  764.26   785.2  780.06   833.2  792.83   842.8  795.84   871.6  806.95
#Mann= 3 , 0 , 0
       0      .1       0     294    .045       0     475      .1       0
Bank Sta=294,475
XS Rating Curve= 0 ,0
Exp/Cntr=0.3,0.1

Type RM Length L Ch R = 1 ,1453.4  ,270.8,276,281.3
XS GIS Cut Line= 4
     1742372.134       516417.46     1742799.218       516417.46
     1743215.884      516302.876     1743695.051      516089.335
#Sta/Elev= 30
       0  833.72   135.9  799.86   242.7   777.9   252.4  773.97   262.1  767.92
   300.9  740.94   310.6  736.02   359.1  717.04   368.8  713.71     398  709.03
   417.4  702.57   436.9   699.7     476 686.954   702.1  685.87     725 686.057
   741.4  686.61   790.5  699.76   819.9  703.49   878.6  720.55   917.5  729.14
   956.4   744.5   975.8  753.68  1024.4  782.12  1043.8  791.95  1131.2   816.5
  1160.4  822.03  1189.5  825.77  1247.8  827.84  1354.7  840.83  1383.8  842.53
#Mann= 3 , 0 , 0
       0      .1       0     476    .045       0     725      .1       0
Bank Sta=476,725
XS Rating Curve= 0 ,0
Exp/Cntr=0.3,0.1

Type RM Length L Ch R = 1 ,1177.4  ,441.5,440.2,439
XS GIS Cut Line= 5
     1741710.676      517016.418     1742382.551      516625.793
     1742820.051      516683.085     1743283.593      516584.126
     1743741.926      516422.668
#Sta/Elev= 30
       0  792.23     118  806.98   177.1  824.03   216.4  829.36   344.3  812.88
   393.5   812.8   442.7  818.13   462.4  817.56   560.8  798.28   600.1  793.94
     669  793.33   777.2  800.65   855.6  794.87   983.1  778.56  1041.9  755.78
  1130.2  715.49  1169.4  707.28  1208.6   694.7    1257 687.123  1508.6   685.5
    1600 686.013  1653.7  691.01  1692.4  703.88  1750.7  715.29  1828.5  765.22
  1906.2     791  1945.1  797.56  1993.7  810.39  2042.3  812.95  2178.3  834.26
#Mann= 3 , 0 , 0
       0      .1       0    1257    .045       0    1600      .1       0
Bank Sta=1257,1600
XS Rating Curve= 0 ,0
Exp/Cntr=0.3,0.1

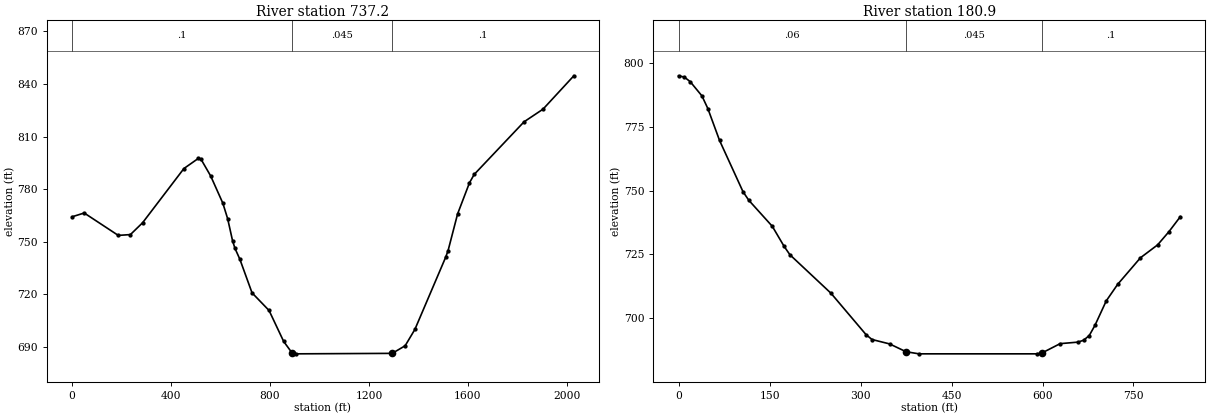
Type RM Length L Ch R = 1 ,737.2   ,558.4,556.3,554.2
XS GIS Cut Line= 6
     1742351.301      517646.626     1742794.009      517391.418
     1742846.093      517131.001     1743439.843      516995.585
     1743809.634      517052.876     1744064.843      516969.543
#Sta/Elev= 30
       0  764.25    49.1  766.41   186.7  753.64   235.8   754.1     285  760.84
     452  791.76     511  797.61   520.8  797.16   560.2  787.54   609.4  772.01
     629  763.09   648.7  750.56   658.5  746.23   678.2  740.05   727.4  720.88
   796.2  710.83   855.2  693.19     888  686.84   904.3   686.1    1294 686.369
  1346.3  690.71  1385.6  700.01  1510.3  741.26  1519.9  745.02  1558.3   765.9
  1606.3  783.64  1625.4  788.41  1826.9  818.41  1903.6  825.63  2028.2  844.66
#Mann= 3 , 0 , 0
       0      .1       0     888    .045       0    1294      .1       0
Bank Sta=888,1294
XS Rating Curve= 0 ,0
Exp/Cntr=0.3,0.1

Type RM Length L Ch R = 1 ,180.9   ,177.6,180.9,184.1
XS GIS Cut Line= 4
     1742882.551       517636.21     1743190.328      517606.858
     1743528.435      517520.369     1743650.553      517403.446
#Sta/Elev= 30
       0  794.92     9.7  794.39    19.3   792.6    38.6  787.04    48.3   782.1
    67.6  769.62   106.3  749.54   115.9  746.18   154.6     736   173.9  728.22
   183.6  724.88   251.2  709.84   309.2  693.59   318.9  691.71     348  689.98
     375 686.928   396.4   686.1   590.3   686.1   599.1  686.44   629.1  690.09
   658.2  690.68   667.6  691.41     677  693.24   686.4  697.21   705.1  706.83
   723.9   713.3   761.5   723.7   789.7  728.73   808.4   733.9   827.2  739.78
#Mann= 3 , 0 , 0
       0     .06       0     375    .045       0   599.1      .1       0
Bank Sta=375,599.1
XS Rating Curve= 0 ,0
Exp/Cntr=0.3,0.1

Chan Stop Cuts=-1
Use User Specified Reach Order=0
Composite Channel Slope=5